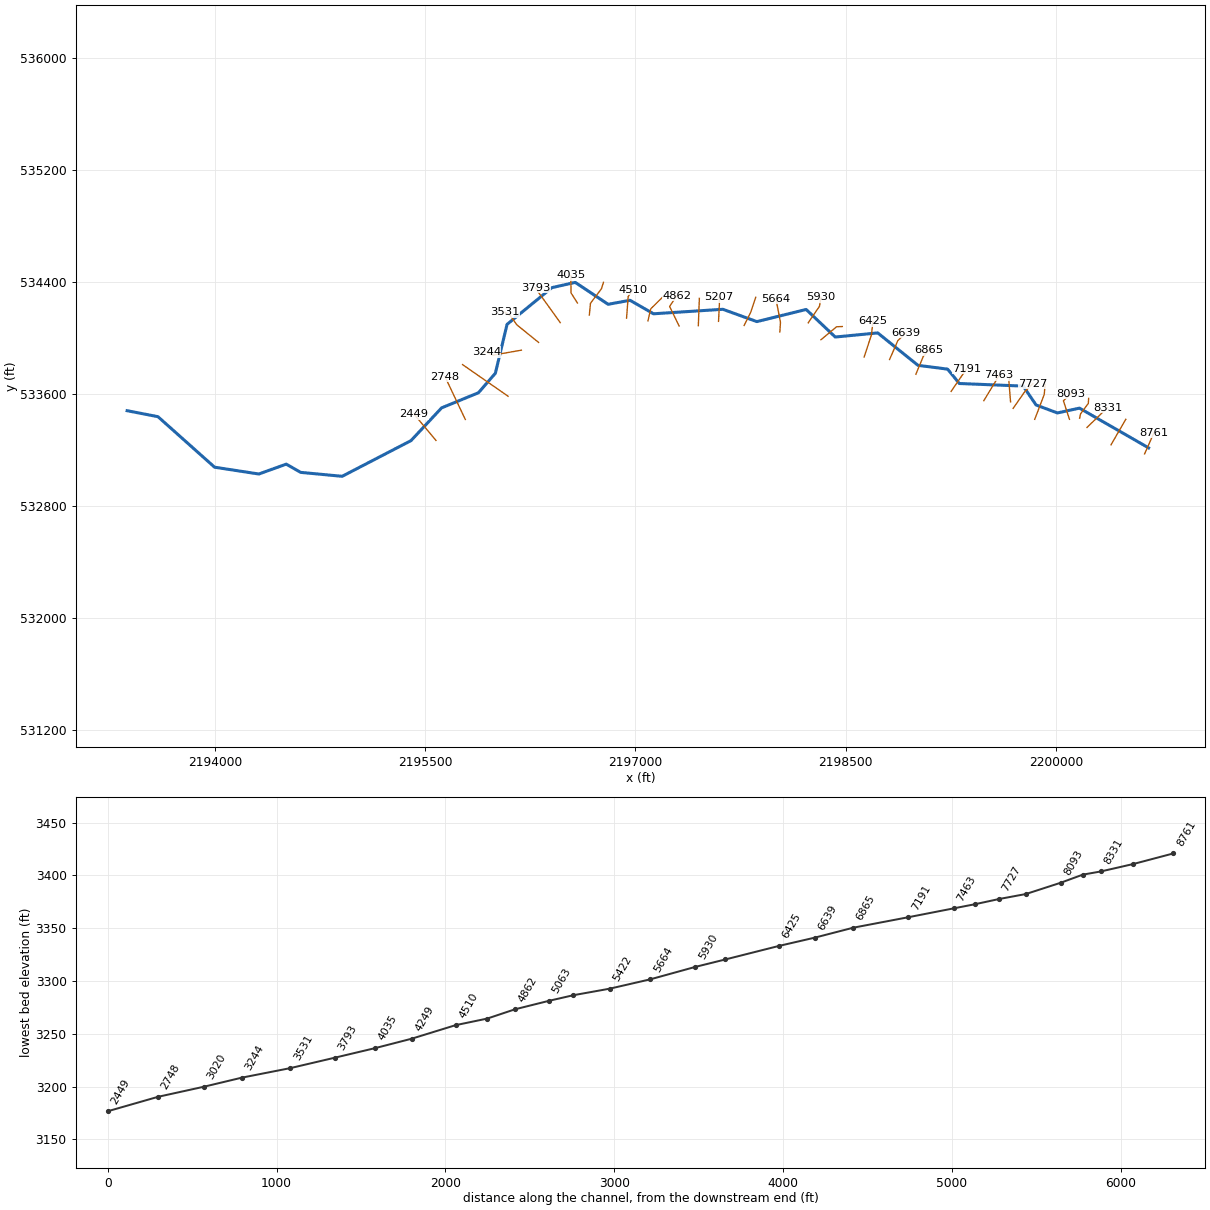
--- LEATHERWCK.prj (project) ---

Proj Title=LEATHERWCK
Current Plan=p01
Default Exp/Contr=0,0
English Units
Geom File=g01
Flow File=f01
Plan File=p01
Y Axis Title=Elevation
X Axis Title(PF)=Main Channel Distance
X Axis Title(XS)=Station
BEGIN DESCRIPTION:
----------MODEL BY WOOD PLC 2022----------
AFH study
Randolph County, WV
HEC-RAS Version: RAS 6.2
Vertical Datum: NAVD88
Projection: NAD 1983 StatePlane West Virginia S FIPS 4702 (US Feet)
Terrain: 1-meter LIDAR (FEMA Region III 3DEP collected 2016-2018)
Land Use: 2019 NLCD
Hydrologic Method:
WV SIR2010-5033 regression equations
Additional Model Notes:
Main stem is out of county boundary
END DESCRIPTION:
DSS Export Rating Curves= 0
DSS Export Rating Curve Sorted= 0
DSS Export Volume Flow Curves= 0
DXF OffsetX= 0
DXF OffsetY= 0
DXF ScaleX= 0
DXF ScaleY= 0

--- LEATHERWCK.p01 (plan) ---

Plan Title=Floodplain
Program Version=6.20
Short Identifier=Floodplain
Geom File=g01
Flow File=f01
Subcritical Flow
K Sum by GR= 0
Std Step Tol= 0.01
Critical Tol= 0.01
Num of Std Step Trials= 20
Max Error Tol= 0.3
Flow Tol Ratio= 0.001
Split Flow NTrial= 30
Split Flow Tol= 0.02
Split Flow Ratio= 0.02
Log Output Level= 0
Friction Slope Method= 1
Unsteady Friction Slope Method= 2
Unsteady Bridges Friction Slope Method= 1
Parabolic Critical Depth
Global Vel Dist= 0 , 0 , 0
Global Log Level= 0
CheckData=True
Encroach Param=-1 ,0,0, 0
Mapping Interval=1HOUR
Computation Time Step Use Courant=        0
Computation Time Step Use Time Series=    0
Computation Time Step Count To Double=0
Computation Time Step Max Doubling=0
Computation Time Step Max Halving=0
Computation Time Step Residence Courant=0
Run HTab= 0
Run UNet= 0
Run Sediment= 0
Run PostProcess= 0
Run WQNet= 0
Run RASMapper=-1
UNET Theta= 0
UNET Theta Warmup= 0
UNET ZTol= 0
UNET ZSATol= 0
UNET MxIter= 0
UNET Max Iter WO Improvement= 0
UNET MaxInSteps= 0
UNET DtIC= 0
UNET DtMin= 0
UNET MaxCRTS= 0
UNET WFStab= 0
UNET SFStab= 0
UNET WFX= 1
UNET SFX= 1
UNET Gravity=32.174
UNET 1D Methodology=Finite Difference
UNET DSS MLevel= 1
UNET Pardiso=0
UNET DZMax Abort= 0
UNET Use Existing IB Tables= 0
UNET Froude Reduction=False
UNET Froude Limit= 0
UNET Froude Power= 0
UNET D1 Cores= 0
UNET WindReference=Eulerian
UNET WindDragFormulation=Hsu (1988)
UNET D2 Coriolis=0
UNET D2 Cores= 0
UNET D2 Theta= 1
UNET D2 Theta Warmup= 1
UNET D2 Z Tol= 0.01
UNET D2 Volume Tol= 0.01
UNET D2 Max Iterations= 20
UNET D2 Equation= 0
UNET D2 RampUpFraction=0.1
UNET D2 TimeSlices= 1
UNET D2 Turbulence Formulation=Non-Conservative (original)
UNET D2 Eddy Viscosity=0.3
UNET D2 Transverse Eddy Viscosity=0.1
UNET D2 Smagorinsky Mixing=0
UNET D2 BCVolumeCheck=0
UNET D2 Cores=0
UNET D2 SolverType=PARDISO (Direct)
UNET D2 Minimum Iterations= 2147483647
UNET D2 Maximum Iterations= 2147483647
UNET D2 Restart Number= 10
UNET D2 Relaxation Coeff=1.3
UNET D2 SOR Precondition Iterations= 10
UNET D2 ILUT Maximum Fill= 8
UNET D2 ILUT Tolerance=1E-08
UNET D1D2 MaxIter= 0
UNET D1D2 ZTol=0.01
UNET D1D2 QTol=0.1
UNET D1D2 MinQTol=1
Write IC File= 0
Write IC File at Fixed DateTime=0
Write IC File at Sim End=0
Echo Input=False
Echo Parameters=False
Echo Output=False
Write Detailed= 0
HDF Write Warmup=0
HDF Write Time Slices=0
HDF Flush=0
HDF Compression= 1
HDF Chunk Size= 1
HDF Spatial Parts= 1
HDF Use Max Rows=0
HDF Fixed Rows= 1
Calibration Method= 0
Calibration Iterations= 20
Calibration Max Change=0.05
Calibration Tolerance=0.2
Calibration Maximum=1.5
Calibration Minimum=0.5
Calibration Optimization Method= 1
WQ AD Non Conservative
WQ ULTIMATE=-1
WQ Max Comp Step=1HOUR
WQ Output Interval=15MIN
WQ Output Selected Increments= 0
WQ Output face flow=0
WQ Output face velocity=0
WQ Output face area=0
WQ Output face dispersion=0
WQ Output cell volume=0
WQ Output cell surface area=0
WQ Output cell continuity=0
WQ Output cumulative cell continuity=0
WQ Output face conc=0
WQ Output face dconc_dx=0
WQ Output face courant=0
WQ Output face peclet=0
WQ Output face adv mass=0
WQ Output face disp mass=0
WQ Output cell mass=0
WQ Output cell source sink temp=0
WQ Output nsm pathways=0
WQ Output nsm derived pathways=0
WQ Create Restart=0
WQ Fixed Restart=0
WQ System Summary=0
WQ Write To DSS=0
Sorting and Armoring Iterations= 10
XS Update Threshold= 0.02
Bed Roughness Predictor= 0
Hydraulics Update Threshold= 0.02
Energy Slope Method= 1
Volume Change Method= 1
Sediment Retention Method= 0
Sediment TS Multiplier= 1
Warm Up Method= 0
XS Weighting Method= 0
Number of US Weighted Cross Sections= 1
Number of DS Weighted Cross Sections= 1
Upstream XS Weight=0
Main XS Weight=1
Downstream XS Weight=0
Number of DS XS's Weighted with US Boundary= 1
Upstream Boundary Weight= 1
Weight of XSs Associated with US Boundary= 0
Number of US XS's Weighted with DS Boundary= 1
Downstream Boundary Weight= 0.5
Weight of XSs Associated with DS Boundary= 0.5
Percentile Method= 0
Sediment Output Level= 3
Mass or Volume Output= 0
Output Increment Type= 1
Profile and TS Output Increment= 1
Transport Output Increment 1
XS Output Flag= 0
XS Output Increment= 10
Read HDF5 Sediment Hotstart= 0
Sediment Hotstart Type= 0
Write Gradation File= 0
Read Gradation Hotstart= 0
Write HDF5 File= 1
Write Binary Output= 1
Write DSS Sediment File= 0
DSS Sediment Output Type= 1
SV Curve= 0
Specific Gage Flag= 0
Subcell Erosion Methods= 0
Subcell Deposition Methods= 0
Advection Scheme= 1
Matrix Solver= 0
Implicit Weighting Factor= 1
Maximum Outer Loop Convergence Iterations= 5
Convergence Maximum Absolute= 0.001
Convergence RMSE= 0.0001
Grain Fractions Max Abs Error= 0.001
Max Subgrid Regions= 1
Max Subgrid Length Scale= 3.402823E+38
Initial Layer Thickness= 3.402823E+38
Min Layer Thickness= 3.402823E+38
Max Layer Thickness= 3.402823E+38
Number of Layers= 5

--- LEATHERWCK.f01 (steady flow) ---

Flow Title=Flow
Program Version=6.20
Number of Profiles= 1
Profile Names=P100yr
River Rch & RM=LEATHERWCK,Main,8761
     350
River Rch & RM=LEATHERWCK,Main,6639
     413
River Rch & RM=LEATHERWCK,Main,4035
     477
River Rch & RM=LEATHERWCK,Main,2748
     533
Boundary for River Rch & Prof#=LEATHERWCK,Main            , 1
Up Type= 0
Dn Type= 3
Dn Slope=0.04101
DSS Import GetInterval= 0
DSS Import GetPeak= 0
DSS Import FillOption= 0

--- LEATHERWCK.g01 (geometry) ---

Geom Title=Geometry
Program Version=6.20

River Reach=LEATHERWCK      ,Main
Reach XY= 30
 2200660.7556946533215.144589941     2200167.183      533498.701
     2200009.891      533464.327     2199857.671      533521.357
     2199766.141      533655.993     2199310.282      533674.396
     2199226.949      533776.827     2199015.143       533804.17
2198728.05798066534035.300019342     2198425.299      534005.993
       2198217.4      534202.608     2197866.108      534116.033
     2197622.782       534203.91     2197128.424      534171.792
     2196960.889      534268.146     2196804.639        534239.5
     2196570.265       534395.75     2196404.032      534358.424
     2196083.719      534096.271     2196000.386      533747.747
     2195879.726      533608.4242195616.94400384533500.692243272
      2195398.39      533266.844     2194907.331       533012.33
     2194611.584      533040.351     2194508.198      533099.205
     2194313.233      533028.719       2193997.3      533077.194
      2193593.13      533437.757     2193373.292      533480.351

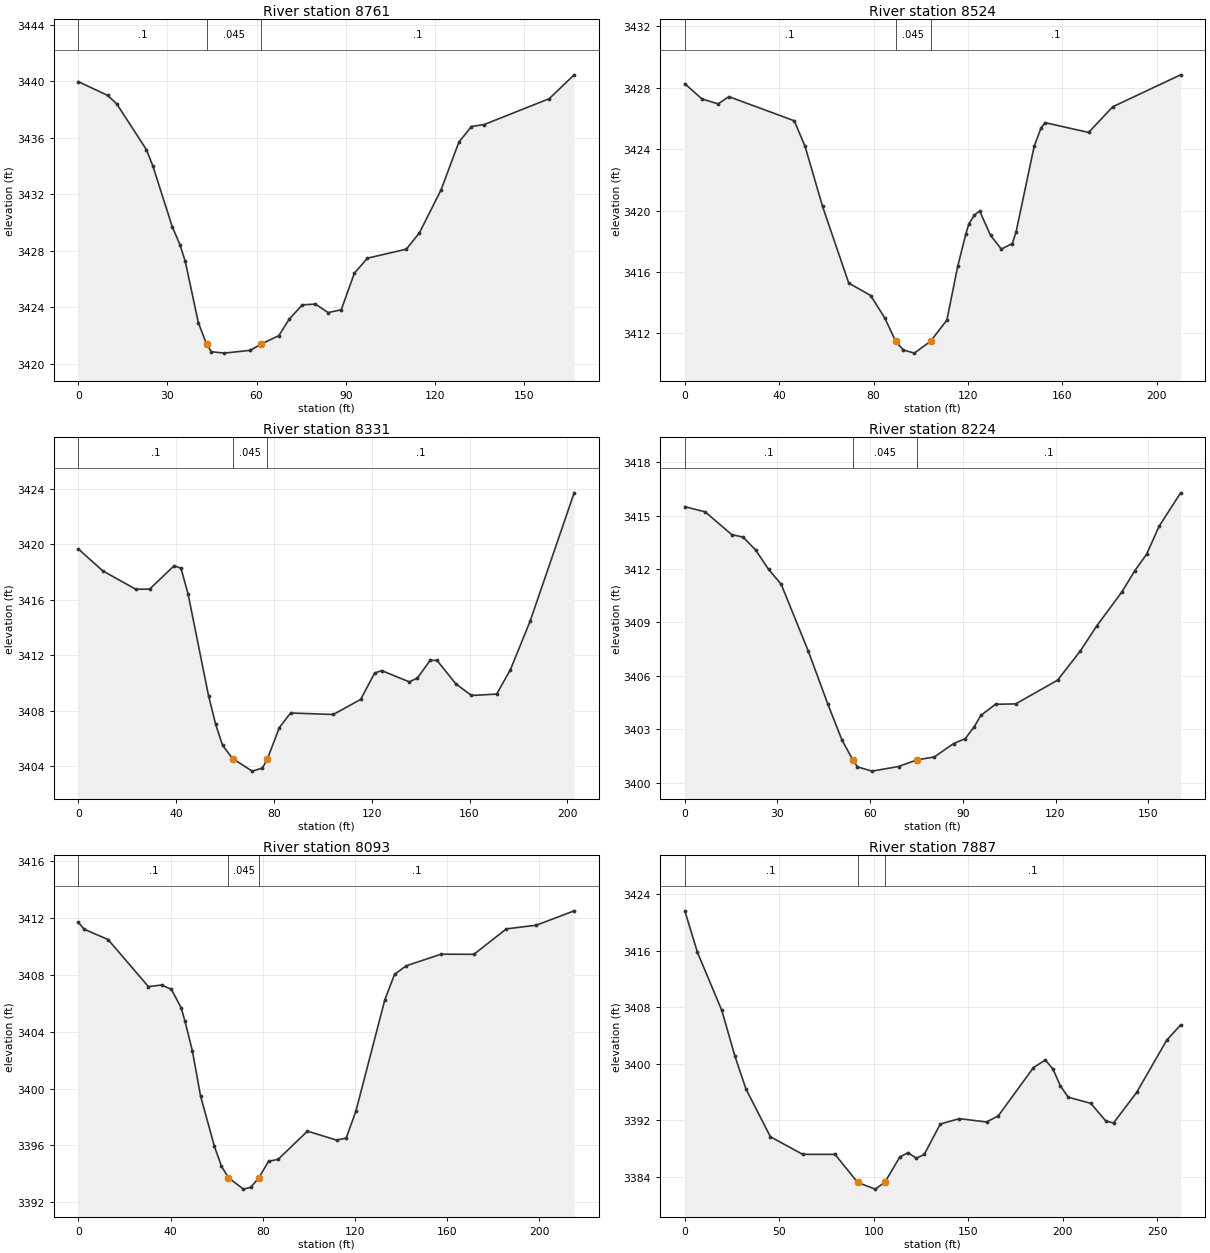
Type RM Length L Ch R = 1 ,8761    ,237.3,237.3,237.3
XS GIS Cut Line= 2
2200632.03844155533172.2527035652200699.64998523533324.812084169
#Sta/Elev= 30
       0 3439.96     9.9 3438.98    12.9 3438.39    22.9 3435.15    25.1 3433.98
    31.6  3429.7    34.2 3428.42      36 3427.23    40.4  3422.9   43.153421.378
    44.8 3420.84    49.1 3420.74    57.9 3420.94   61.543421.379    67.5 3421.98
      71 3423.15    75.4 3424.16    79.8 3424.21    84.1 3423.61    88.5 3423.81
    92.9 3426.39    97.3 3427.46   110.4  3428.1   114.8 3429.25   122.1  3432.3
   128.1 3435.68   132.3 3436.78   136.6 3436.92   158.5 3438.75   166.9 3440.44
#Mann= 3 ,-1,0
       0      .1       0   43.15    .045       0   61.54      .1       0
Bank Sta=43.15,61.54
XS Rating Curve= 0 ,0
Exp/Cntr(USF)=0,0
Exp/Cntr=0.3,0.1

Type RM Length L Ch R = 1 ,8524    ,192.5,192.5,192.5
XS GIS Cut Line= 2
2200392.51925874533237.0111674682200497.82118811533418.935232442
#Sta/Elev= 30
       0 3428.25     7.3 3427.26    14.1 3426.94    18.7 3427.41    46.4 3425.84
      51 3424.17    58.4 3420.27    69.5 3415.28    78.8 3414.47    84.8    3413
    89.43411.491    92.6 3410.93    97.3 3410.72  104.183411.491   111.1 3412.87
   115.7 3416.37   119.1 3418.45   120.4 3419.12   122.8 3419.71     125 3419.97
   129.6 3418.39   134.2 3417.49   138.8 3417.85   140.4 3418.58   148.1 3424.17
     151 3425.36   152.7 3425.72   171.2 3425.08   181.4 3426.75   210.2 3428.83
#Mann= 3 ,-1,0
       0      .1       0    89.4    .045       0  104.18      .1       0
Bank Sta=89.4,104.18
XS Rating Curve= 0 ,0
Exp/Cntr(USF)=0,0
Exp/Cntr=0.3,0.1

Type RM Length L Ch R = 1 ,8331    ,107.1,107.1,107.1
XS GIS Cut Line= 2
2200221.03903214533360.8809539492200367.00634074 533501.71158307
#Sta/Elev= 30
       0 3419.67     9.9  3418.1    23.5 3416.76    29.2 3416.78    39.2 3418.46
      42 3418.27    44.9 3416.41    53.3 3409.06    56.2 3407.02      59 3405.51
   63.143404.562    71.1 3403.66    75.3 3403.88   77.373404.563    82.2 3406.79
    86.8 3407.85   104.3 3407.74   115.5 3408.83   121.2 3410.73   124.1  3410.9
   135.4 3410.09   138.7 3410.37   143.9 3411.64   146.7 3411.64   154.4 3409.95
   160.8 3409.11   171.1 3409.21   176.7 3410.96   184.8 3414.47   202.8 3423.71
#Mann= 3 ,-1,0
       0      .1       0   63.14    .045       0   77.37      .1       0
Bank Sta=63.14,77.37
XS Rating Curve= 0 ,0
Exp/Cntr(USF)=0,0
Exp/Cntr=0.3,0.1

Type RM Length L Ch R = 1 ,8224    ,131.5,131.5,131.5
XS GIS Cut Line= 4
2200168.42709565533426.7565580252200175.36161295533457.961885876
2200230.49102549533532.1612209882200232.91810654533568.220710949
#Sta/Elev= 30
       0 3415.51     6.6 3415.22    15.2 3413.94    18.9  3413.8      23 3413.06
    27.1 3411.99    31.2 3411.15      40 3407.38    46.3 3404.41    50.9 3402.38
    54.4 3401.27    55.9 3400.88    60.6 3400.64    69.2  3400.9    75.1 3401.27
    80.8 3401.44      87 3402.19    90.8 3402.47    93.7 3403.14    95.8 3403.77
   100.6  3404.4   107.1 3404.42   120.7 3405.76     128 3407.39   133.4 3408.82
   141.5 3410.72   145.7 3411.92   149.5 3412.84   153.5  3414.4   160.5 3416.29
#Mann= 3 ,-1,0
       0      .1       0    54.4    .045       0    75.1      .1       0
Bank Sta=54.4,75.1
XS Rating Curve= 0 ,0
Exp/Cntr(USF)=0,0
Exp/Cntr=0.3,0.1

Type RM Length L Ch R = 1 ,8093    ,205.6,205.6,205.6
XS GIS Cut Line= 3
2200096.18057636533418.7747319562200052.70984095533551.314824005
2200108.26768625533602.632342025
#Sta/Elev= 30
       0  3411.7     2.5 3411.22    12.9 3410.49    30.4 3407.18    36.2 3407.29
    40.4 3406.98    44.6 3405.69    46.3 3404.73    49.5 3402.64      53  3399.5
      59 3395.96    62.1 3394.54   65.133393.735    71.6 3392.93    74.8 3393.06
   78.353393.734    82.5 3394.88    86.7 3395.03    99.4 3397.01     112 3396.38
   116.2 3396.52   120.4 3398.41     133 3406.27   137.2 3408.04   142.2 3408.64
   157.4 3409.46   171.6 3409.45   185.7 3411.24   198.7  3411.5   215.1 3412.51
#Mann= 3 ,-1,0
       0      .1       0   65.13    .045       0   78.35      .1       0
Bank Sta=65.13,78.35
XS Rating Curve= 0 ,0
Exp/Cntr(USF)=0,0
Exp/Cntr=0.3,0.1

Type RM Length L Ch R = 1 ,7887    ,159.7,159.7,159.7
XS GIS Cut Line= 3
2199848.27050951533418.8858416532199916.02647913533596.023696987
2199922.26664656533668.538441928
#Sta/Elev= 30
       0 3421.66     6.7 3415.79    19.6 3407.56    26.5 3401.13    32.4 3396.44
    45.3  3389.7    62.4 3387.21    79.5 3387.21    91.5 3383.23   100.8 3382.29
  105.91 3383.27   113.8 3386.84   118.1 3387.45   122.5 3386.67   126.7 3387.19
   135.2  3391.5   145.3 3392.26   159.7 3391.79   165.9 3392.65   184.5 3399.48
   190.8 3400.56   194.8 3399.29   198.8 3396.89   202.9  3395.3   214.9 3394.42
   222.9  3391.9   226.9 3391.65   239.1 3395.96   255.1 3403.39   262.4 3405.51
#Mann= 3 ,0,0
       0      .1       0    91.5    .045       0  105.91      .1       0
Bank Sta=91.5,105.91
XS Rating Curve= 0 ,0
Exp/Cntr(USF)=0,0
Exp/Cntr=0.3,0.1

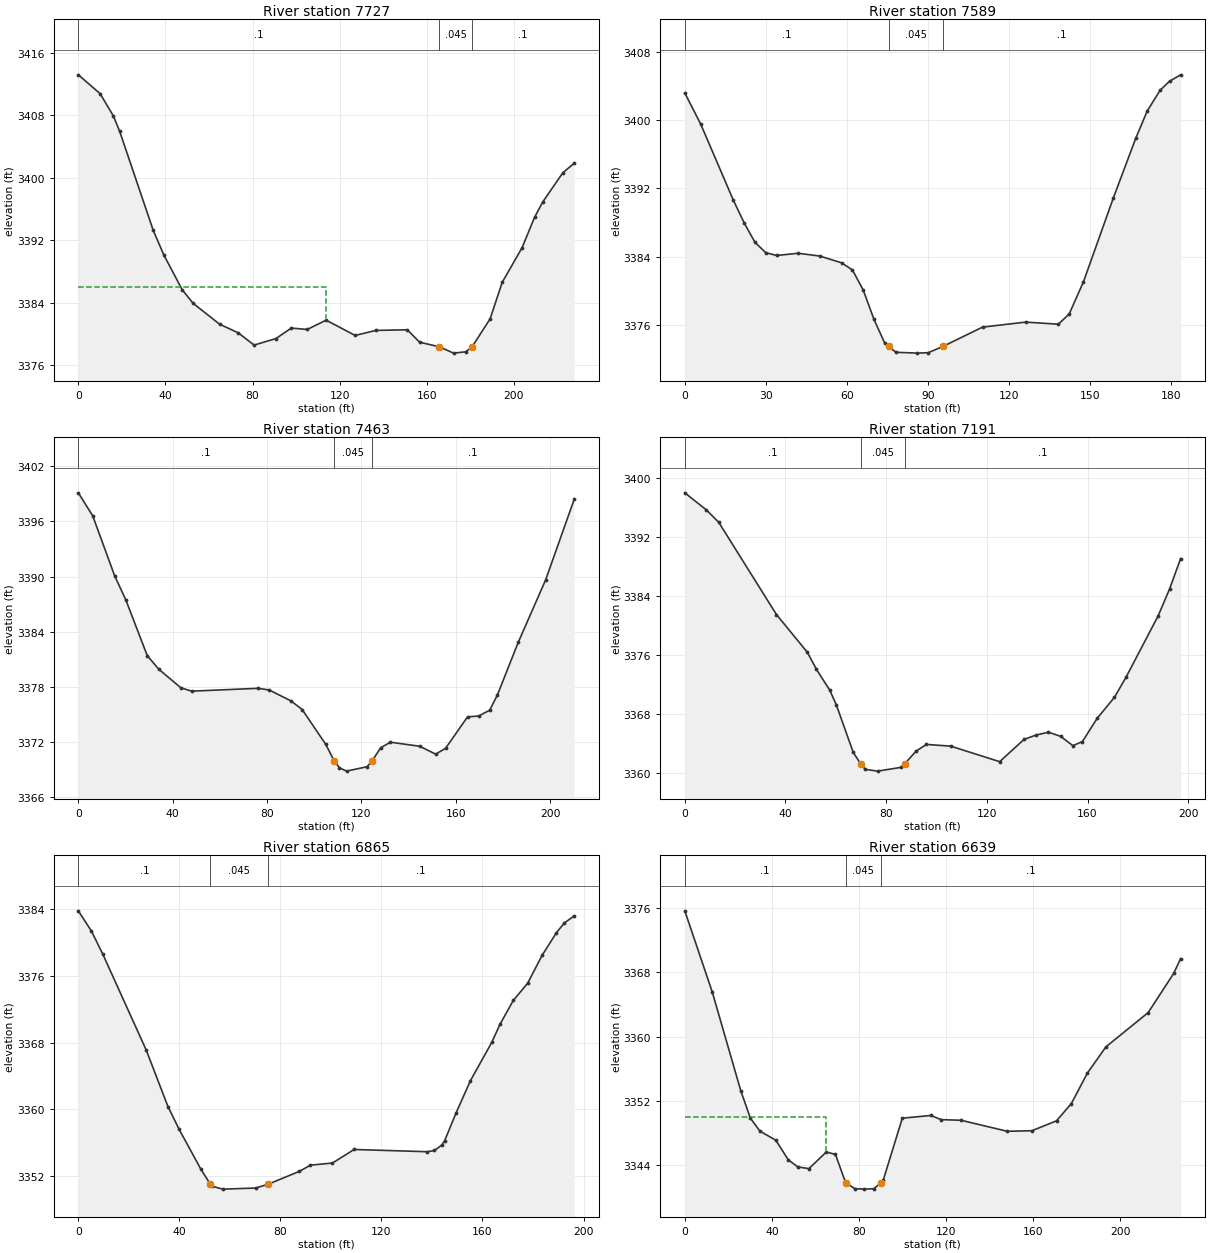
Type RM Length L Ch R = 1 ,7727    ,138.8,138.8,138.8
XS GIS Cut Line= 3
2199694.00269031533496.9582820432199778.45397674  533618.0534751
2199835.87400563533673.839993627
#Sta/Elev= 30
       0 3413.17      10 3410.76    16.1  3407.9      19 3405.92    34.4 3393.25
    39.3 3390.08    47.7 3385.65    52.7 3383.91    64.9 3381.23    73.5 3380.12
    80.7 3378.56    90.8  3379.4    97.8 3380.74   105.1 3380.56   113.8 3381.75
   127.1  3379.8   136.7 3380.44   151.1 3380.52   156.7 3378.93  165.78 3378.34
   172.3 3377.53   177.9  3377.7   180.8 3378.33   189.1 3381.92   194.7 3386.62
   203.8 3391.04   209.5 3394.91   213.3  3396.9   222.5 3400.63   227.7 3401.84
#Mann= 3 ,0,0
       0      .1       0  165.78    .045       0   180.8      .1       0
#XS Ineff= 2 , 0
           113.8    3386
Permanent Ineff=
       F       F
Bank Sta=165.78,180.8
XS Rating Curve= 0 ,0
Exp/Cntr(USF)=0,0
Exp/Cntr=0.3,0.1

Type RM Length L Ch R = 1 ,7589    ,126.1,126.1,126.1
XS GIS Cut Line= 3
2199675.87847638533543.2753426642199663.86587577 533690.51303456
2199673.65137496533725.100588561
#Sta/Elev= 30
       0 3403.16     5.9 3399.51      18 3390.61      22 3387.96      26 3385.69
      30 3384.48      34 3384.15      42 3384.41    50.1 3384.08    58.1 3383.29
    62.1 3382.46    66.1 3380.11    70.1 3376.67    74.1 3373.8875.528023373.514
    78.2 3372.83    86.2 3372.73    90.2 3372.78   95.62 3373.51   110.3 3375.77
   126.3 3376.36   138.4 3376.11   142.4  3377.3   147.7 3381.07   158.8  3390.9
   167.1 3397.88   171.3 3401.03   176.1 3403.48   179.6 3404.53   183.7 3405.28
#Mann= 3 ,0,0
       0      .1       075.52802    .045       0   95.62      .1       0
Bank Sta=75.52802,95.62
XS Rating Curve= 0 ,0
Exp/Cntr(USF)=0,0
Exp/Cntr=0.3,0.1

Type RM Length L Ch R = 1 ,7463    ,271.9,271.9,271.9
XS GIS Cut Line= 2
2199485.28410162533551.9966546352199594.09866987533731.886573609
#Sta/Elev= 30
       0 3399.12     6.1 3396.61    15.4 3390.08    20.1 3387.48    29.2  3381.4
    34.1 3379.91    43.5 3377.88    48.1 3377.52    76.2 3377.83    80.9 3377.65
    90.2 3376.45    94.9 3375.52   104.9 3371.72  108.45 3369.94   110.7 3369.18
   113.7 3368.81   122.4 3369.29  124.57 3369.94   128.2 3371.36   132.3 3371.96
   144.7 3371.52   151.5 3370.66   155.7  3371.3     165 3374.72   169.7 3374.81
   174.4 3375.45   177.7 3377.13   186.5 3382.84   198.1 3389.63   210.2  3398.4
#Mann= 3 ,0,0
       0      .1       0  108.45    .045       0  124.57      .1       0
Bank Sta=108.45,124.57
XS Rating Curve= 0 ,0
Exp/Cntr(USF)=0,0
Exp/Cntr=0.3,0.1

Type RM Length L Ch R = 1 ,7191    ,325.9,325.9,325.9
XS GIS Cut Line= 2
2199251.59858331533618.0499059572199363.01759064533780.468712816
#Sta/Elev= 30
       0 3398.01     8.6 3395.69    13.5 3394.01    36.4 3381.53    48.7 3376.41
    52.3 3374.11    57.6 3371.28    60.2  3369.3    66.9 3362.88   69.85 3361.32
    71.7 3360.56    76.6 3360.32    85.9 3360.83   87.46 3361.34    91.9 3363.03
      96 3363.94   105.7  3363.7   125.1  3361.6   134.8 3364.62   139.6 3365.21
   144.5 3365.59   149.3 3365.03   154.2 3363.77     158 3364.33   163.8 3367.45
   170.7 3370.31   175.3 3373.03   188.1 3381.37   192.6 3384.98     197 3389.11
#Mann= 3 ,0,0
       0      .1       0   69.85    .045       0   87.46      .1       0
Bank Sta=69.85,87.46
XS Rating Curve= 0 ,0
Exp/Cntr(USF)=0,0
Exp/Cntr=0.3,0.1

Type RM Length L Ch R = 1 ,6865    ,226.2,226.2,226.2
XS GIS Cut Line= 3
2199000.24153659533740.3843244312199053.61649828533868.272846503
2199091.13751095533912.135438784
#Sta/Elev= 30
       0 3383.82     5.2 3381.38     9.7 3378.61    26.9 3367.09    35.5 3360.31
    39.9 3357.59    48.5 3352.81   52.293350.985    52.9 3350.76    57.2 3350.41
    70.2 3350.54   75.033350.986    87.5 3352.54    91.9 3353.29   100.6 3353.54
   109.2 3355.17   138.2  3354.9     141 3355.05   143.9  3355.7     145  3356.2
   149.5 3359.52   155.2 3363.41   163.7 3368.04   167.1 3370.29   172.2 3373.06
   177.9 3375.13   183.6 3378.47   189.3  3381.2   192.4 3382.36   196.3  3383.2
#Mann= 3 ,-1,0
       0      .1       0   52.29    .045       0   75.03      .1       0
Bank Sta=52.29,75.03
XS Rating Curve= 0 ,0
Exp/Cntr(USF)=0,0
Exp/Cntr=0.3,0.1

Type RM Length L Ch R = 1 ,6639    ,213.2,213.2,213.2
XS GIS Cut Line= 3
2198812.66490463 533845.615862272198871.85298096533980.902893884
2198930.51259233534035.334785509
#Sta/Elev= 30
       0 3375.66    12.6 3365.58    25.7  3353.3    30.1 3349.89    34.5 3348.27
    41.8 3347.14    47.5 3344.71    51.9 3343.82      57 3343.61      65 3345.68
    69.2 3345.37   73.863341.856    78.1 3341.12    82.5 3341.06    86.8 3341.11
   90.123341.857    91.2 3342.24    99.9 3349.88     113 3350.22   117.7  3349.7
   126.9 3349.62   148.1 3348.25   159.4 3348.32   170.7 3349.55   177.5 3351.69
   184.9 3355.49   193.4 3358.75   212.8 3363.01   224.5 3367.87   227.7 3369.72
#Mann= 3 ,-1,0
       0      .1       0   73.86    .045       0   90.12      .1       0
#XS Ineff= 2 , 0
              65    3350
Permanent Ineff=
       F       F
Bank Sta=73.86,90.12
XS Rating Curve= 0 ,0
Exp/Cntr(USF)=0,0
Exp/Cntr=0.3,0.1

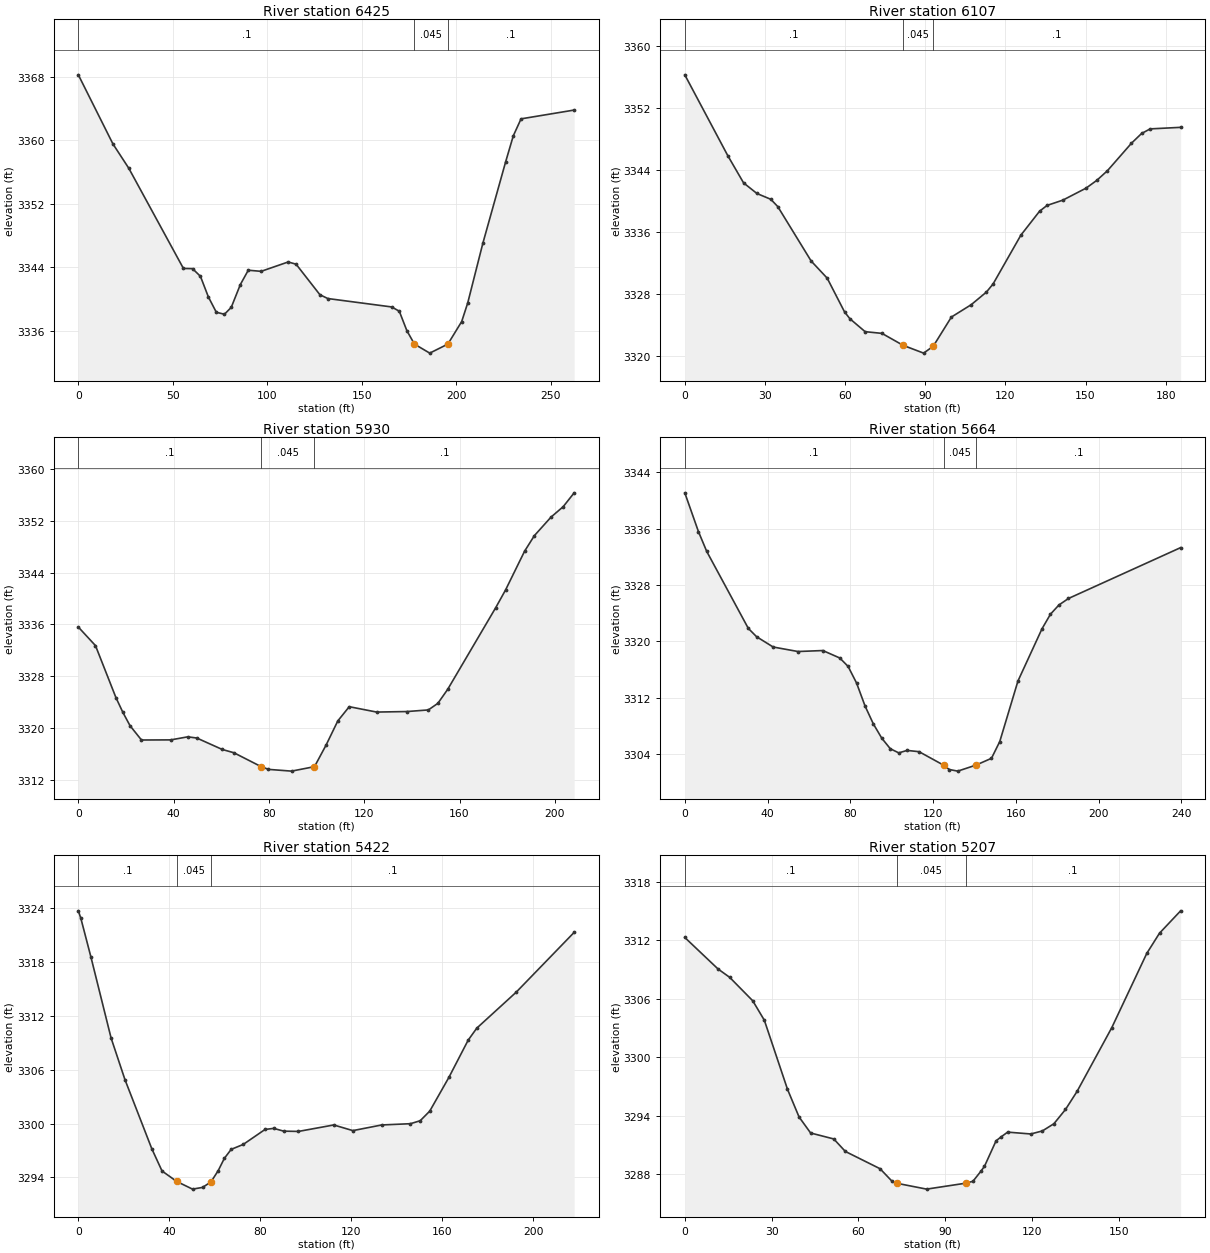
Type RM Length L Ch R = 1 ,6425    ,318.8,318.8,318.8
XS GIS Cut Line= 3
2198631.23811046533863.8532916492198683.49520372534021.293224892
2198693.68691448 534117.14527392
#Sta/Elev= 30
       0 3368.26    18.3 3359.55    26.7 3356.48    55.6 3343.85    60.4 3343.83
    64.6 3342.86    68.8 3340.26      73 3338.33    77.3 3338.08    80.9 3338.95
    85.7 3341.82    89.9 3343.63    96.7 3343.49     111 3344.67   115.2 3344.39
   127.8 3340.54     132 3340.06   165.8    3339   169.8 3338.46   173.8 3336.01
   177.8 3334.32   185.9 3333.18   195.5 3334.32   202.8 3337.16     206 3339.51
     214 3347.03   226.1 3357.33   230.1 3360.57   234.2 3362.71   262.3 3363.82
#Mann= 3 ,0,0
       0      .1       0   177.8    .045       0   195.5      .1       0
Bank Sta=177.8,195.5
XS Rating Curve= 0 ,0
Exp/Cntr(USF)=0,0
Exp/Cntr=0.3,0.1

Type RM Length L Ch R = 1 ,6107    ,176.7,176.7,176.7
XS GIS Cut Line= 3
2198323.44688547533986.9041371662198434.45104474534079.294635973
2198475.59723419534080.850675554
#Sta/Elev= 30
       0 3356.25    16.1 3345.81      22  3342.3      27 3340.93    32.2 3340.18
    34.8 3339.24    47.3 3332.21    53.3    3330    59.8 3325.64    61.8 3324.76
    67.5 3323.09    73.8 3322.87    81.7 3321.33    89.4 3320.32      93 3321.21
    99.8 3324.98   107.2 3326.57   112.9  3328.2   115.4 3329.25   125.8 3335.55
   132.8 3338.64   135.6 3339.39   141.5 3340.07   150.2 3341.62   154.2 3342.62
   158.2 3343.87   167.2 3347.42     171 3348.68   174.2 3349.27   185.6 3349.47
#Mann= 3 ,-1,0
       0      .1       0    81.7    .045       0      93      .1       0
Bank Sta=81.7,93
XS Rating Curve= 0 ,0
Exp/Cntr(USF)=0,0
Exp/Cntr=0.3,0.1

Type RM Length L Ch R = 1 ,5930    ,266.3,266.3,266.3
XS GIS Cut Line= 3
2198232.12816239534107.257452176 2198312.7546331534225.333125027
2198322.74301512534289.688891095
#Sta/Elev= 30
       0 3335.59     7.2 3332.72    15.8 3324.67    18.7  3322.4    21.7 3320.34
    26.5 3318.13    38.8 3318.15    45.9 3318.62    49.7 3318.44    60.4 3316.67
    65.3 3316.16   76.743314.012    79.8 3313.59    89.5 3313.32   99.123314.013
     104 3317.36   108.9 3321.08   113.7 3323.28   125.2 3322.45   137.9 3322.53
   146.9 3322.78   150.9  3323.8     155 3325.95   175.2  3338.6   179.3 3341.32
   187.3 3347.32   191.4 3349.72   198.4 3352.59   203.5  3354.2   208.1 3356.34
#Mann= 3 ,-1,0
       0      .1       0   76.74    .045       0   99.12      .1       0
Bank Sta=76.74,99.12
XS Rating Curve= 0 ,0
Exp/Cntr(USF)=0,0
Exp/Cntr=0.3,0.1

Type RM Length L Ch R = 1 ,5664    ,241.1,241.1,241.1
XS GIS Cut Line= 3
2198029.99031242534042.5733401862198034.27087865534111.062399941
2198001.92882266534278.955720033
#Sta/Elev= 30
       0 3341.08     6.6 3335.57    10.6 3332.76    30.7 3321.83    34.7 3320.65
    42.7 3319.19    54.7 3318.55    66.7 3318.69    74.9 3317.63    78.9 3316.44
      83 3314.08    87.1 3310.82    91.1 3308.28    95.2 3306.24    99.3 3304.75
   103.4 3304.16   107.4 3304.51   113.2 3304.33  125.023302.424   127.8  3301.8
   131.9 3301.57  140.723302.425   148.2 3303.39   152.2 3305.77     161 3314.37
   172.6 3321.77   176.7 3323.85   180.8 3325.16   185.4 3326.08   239.6  3333.3
#Mann= 3 ,-1,0
       0      .1       0  125.02    .045       0  140.72      .1       0
Bank Sta=125.02,140.72
XS Rating Curve= 0 ,0
Exp/Cntr(USF)=0,0
Exp/Cntr=0.3,0.1

Type RM Length L Ch R = 1 ,5422    ,215.6,215.6,215.6
XS GIS Cut Line= 3
2197775.05881222534088.232713356 2197822.1450408534183.356407459
2197857.81642609534289.419326384
#Sta/Elev= 30
       0  3323.7     1.1 3322.87     5.5 3318.59    14.4 3309.53    20.5 3304.89
    32.3 3297.19    36.8 3294.71    43.3 3293.54    50.2 3292.69    54.6 3292.88
    58.3 3293.49    61.5 3294.75    64.2 3296.12    67.2 3297.12    72.5 3297.67
    82.1 3299.34    85.9 3299.46    90.3 3299.15    96.8 3299.12   112.3 3299.84
   120.7 3299.21   133.4 3299.84     146 3299.98   150.3 3300.31   154.5 3301.38
   162.9 3305.13   171.4 3309.29   175.2 3310.63   192.5 3314.63     218  3321.3
#Mann= 3 ,-1,0
       0      .1       0    43.3    .045       0    58.3      .1       0
Bank Sta=43.3,58.3
XS Rating Curve= 0 ,0
Exp/Cntr(USF)=0,0
Exp/Cntr=0.3,0.1

Type RM Length L Ch R = 1 ,5207    ,144.1,144.1,144.1
XS GIS Cut Line= 3
2197592.42131954534117.7210585282197598.60435966534242.808716274
 2197596.2262673534288.943707914
#Sta/Elev= 30
       0 3312.27    11.5 3309.04    15.5 3308.19    23.5 3305.78    27.5 3303.79
    35.5 3296.72    39.5 3293.88    43.5 3292.24    51.5 3291.63    55.5 3290.35
    67.5 3288.58    71.5 3287.34    73.33287.089    83.6 3286.49   97.063287.096
    99.6 3287.29   102.3  3288.3   103.6 3288.83   107.6 3291.44   109.2 3291.81
   111.6 3292.33   119.6 3292.14   123.6 3292.45   127.6 3293.19   131.6 3294.65
   135.6  3296.5   147.6 3303.03   159.7 3310.64   164.1 3312.71   171.4    3315
#Mann= 3 ,-1,0
       0      .1       0    73.3    .045       0   97.06      .1       0
Bank Sta=73.3,97.06
XS Rating Curve= 0 ,0
Exp/Cntr(USF)=0,0
Exp/Cntr=0.3,0.1

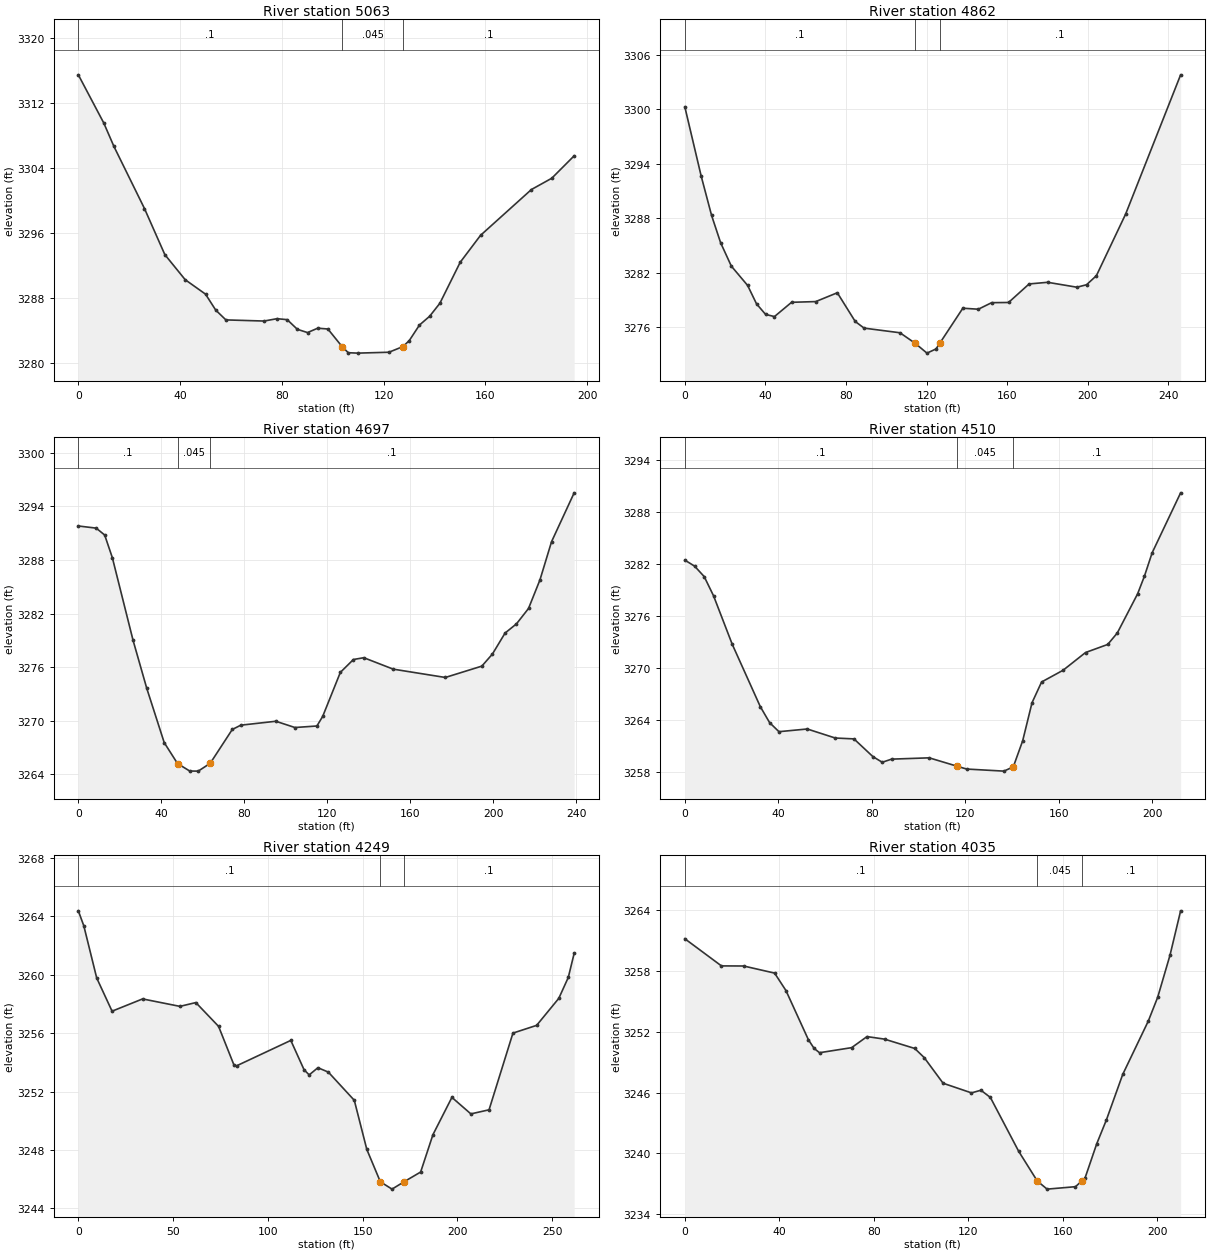
Type RM Length L Ch R = 1 ,5063    ,201.2,201.2,201.2
XS GIS Cut Line= 2
2197448.40080515 534087.174993642197455.60586699534281.903033368
#Sta/Elev= 30
       0 3315.46      10 3309.53      14 3306.64      26    3299      34 3293.33
      42 3290.24      50 3288.46      54  3286.5      58 3285.29      73 3285.15
    78.1 3285.44    82.1 3285.32    86.1 3284.13    90.1 3283.73    94.1 3284.27
    98.1 3284.17  103.69    3282   106.1 3281.25   109.8  3281.2   122.1 3281.31
  127.62 3282.01   130.1 3282.75   134.1 3284.66   138.1 3285.74   142.1 3287.33
   150.1 3292.38   158.1  3295.7   178.1 3301.34   186.1 3302.73   194.9 3305.49
#Mann= 3 ,0,0
       0      .1       0  103.69    .045       0  127.62      .1       0
Bank Sta=103.69,127.62
XS Rating Curve= 0 ,0
Exp/Cntr(USF)=0,0
Exp/Cntr=0.3,0.1

Type RM Length L Ch R = 1 ,4862    ,164.8,164.8,164.8
XS GIS Cut Line= 3
2197311.05924211534085.1889756782197243.10097257534224.226047546
2197294.41640059534299.812286118
#Sta/Elev= 30
       0 3300.27     8.1 3292.67    13.3 3288.31    17.8  3285.3    23.1 3282.74
    31.2 3280.61    35.6 3278.59    40.1 3277.43    44.5 3277.19      53 3278.76
      65 3278.84    75.7 3279.81    84.6 3276.65      89 3275.92   106.8 3275.41
  114.313274.259   120.2 3273.17   124.7 3273.63  126.563274.258     138 3278.11
   145.7    3278   152.3 3278.72   160.7 3278.74   170.9 3280.78   180.1 3280.96
   194.6 3280.42   199.4 3280.69   204.3 3281.69   218.8 3288.46   246.1 3303.78
#Mann= 3 ,-1,0
       0      .1       0  114.31    .045       0  126.56      .1       0
Bank Sta=114.31,126.56
XS Rating Curve= 0 ,0
Exp/Cntr(USF)=0,0
Exp/Cntr=0.3,0.1

Type RM Length L Ch R = 1 ,4697    ,187,187,187
XS GIS Cut Line= 3
2197088.90925258534120.8325545622197108.67262689534206.820569084
2197215.81091918534312.918683776
#Sta/Elev= 30
       0  3291.8     8.6 3291.56    12.7 3290.79    16.4 3288.25    26.4 3278.99
      33 3273.62    41.4 3267.56   47.823265.216    53.7 3264.38    57.8 3264.37
   63.583265.248    74.2 3269.03    78.3 3269.51    95.2 3269.95   104.4 3269.25
     115 3269.42   117.8  3270.5   126.3 3275.42   132.6 3276.86   137.6 3277.06
   151.8 3275.78   176.9 3274.85   194.5 3276.12   199.6 3277.47   205.7 3279.82
   211.2 3280.85     217 3282.57   222.5 3285.76   228.1 3290.04     239 3295.51
#Mann= 3 ,-1,0
       0      .1       0   47.82    .045       0   63.58      .1       0
Bank Sta=47.82,63.58
XS Rating Curve= 0 ,0
Exp/Cntr(USF)=0,0
Exp/Cntr=0.3,0.1

Type RM Length L Ch R = 1 ,4510    ,260.4,260.4,260.4
XS GIS Cut Line= 3
2196936.34987198534140.9426547332196947.79182553534294.195487065
2196979.34387924534343.430559896
#Sta/Elev= 30
       0 3282.44     4.2 3281.74     8.3 3280.54    12.3 3278.33    20.3 3272.75
    32.3 3265.58    36.3 3263.73    40.3 3262.69    52.4    3263    64.4 3261.96
    72.4 3261.86    80.5 3259.82    84.5 3259.17    88.5 3259.53   104.6 3259.68
   116.6 3258.71   120.6 3258.39   136.6 3258.15   140.6 3258.65   144.6 3261.64
   148.6 3266.02   152.7 3268.41   161.9 3269.76   171.5  3271.8     181 3272.73
   185.1 3274.05   193.8 3278.56   196.7 3280.58     200 3283.27   212.2 3290.18
#Mann= 3 ,-1,0
       0      .1       0   116.6    .045       0   140.6      .1       0
Bank Sta=116.6,140.6
XS Rating Curve= 0 ,0
Exp/Cntr(USF)=0,0
Exp/Cntr=0.3,0.1

Type RM Length L Ch R = 1 ,4249    ,214.5,214.5,214.5
XS GIS Cut Line= 4
2196670.75785938534163.4798359582196678.73255428 534246.69404356
 2196757.7860515534351.0585289272196771.30836024534396.132891377
#Sta/Elev= 30
       0 3264.37     2.9 3263.34     9.7 3259.77    17.8  3257.5    33.9 3258.34
    53.6 3257.83      62 3258.09      74 3256.46    82.1 3253.82    83.5 3253.76
   112.1  3255.5   119.1 3253.49   121.8 3253.14   126.4 3253.63   131.9 3253.33
   145.6  3251.4   152.2 3248.04  159.343245.824   165.5 3245.32   171.8 3245.82
   180.6 3246.49   187.1 3249.05   197.1  3251.6   207.1 3250.47   216.7 3250.75
   229.3    3256   241.8 3256.53   253.5 3258.38   258.5 3259.81   261.6 3261.46
#Mann= 3 ,-1,0
       0      .1       0  159.34    .045       0   171.8      .1       0
Bank Sta=159.34,171.8
XS Rating Curve= 0 ,0
Exp/Cntr(USF)=0,0
Exp/Cntr=0.3,0.1

Type RM Length L Ch R = 1 ,4035    ,241.4,241.4,241.4
XS GIS Cut Line= 3
 2196585.5141455 534249.080622512196540.03722015534320.633213019
2196538.82051237534445.622666745
#Sta/Elev= 30
       0 3261.17    15.5 3258.49    24.9 3258.48      38 3257.78    42.8 3256.06
    52.3 3251.21    54.7 3250.36      57 3249.93    70.6 3250.43    77.1 3251.52
    84.5 3251.27    97.3 3250.35   101.3 3249.45   109.3 3246.92   121.3 3245.97
   125.3 3246.23   129.3 3245.52   141.3  3240.2  149.143237.283   153.3 3236.48
   165.3 3236.72     1683237.283   169.3 3237.54   174.3 3240.95   178.4 3243.31
   185.3 3247.79   196.1 3253.04   200.1  3255.4   205.3 3259.54   209.8 3263.92
#Mann= 3 ,-1,0
       0      .1       0  149.14    .045       0     168      .1       0
Bank Sta=149.14,168
XS Rating Curve= 0 ,0
Exp/Cntr(USF)=0,0
Exp/Cntr=0.3,0.1

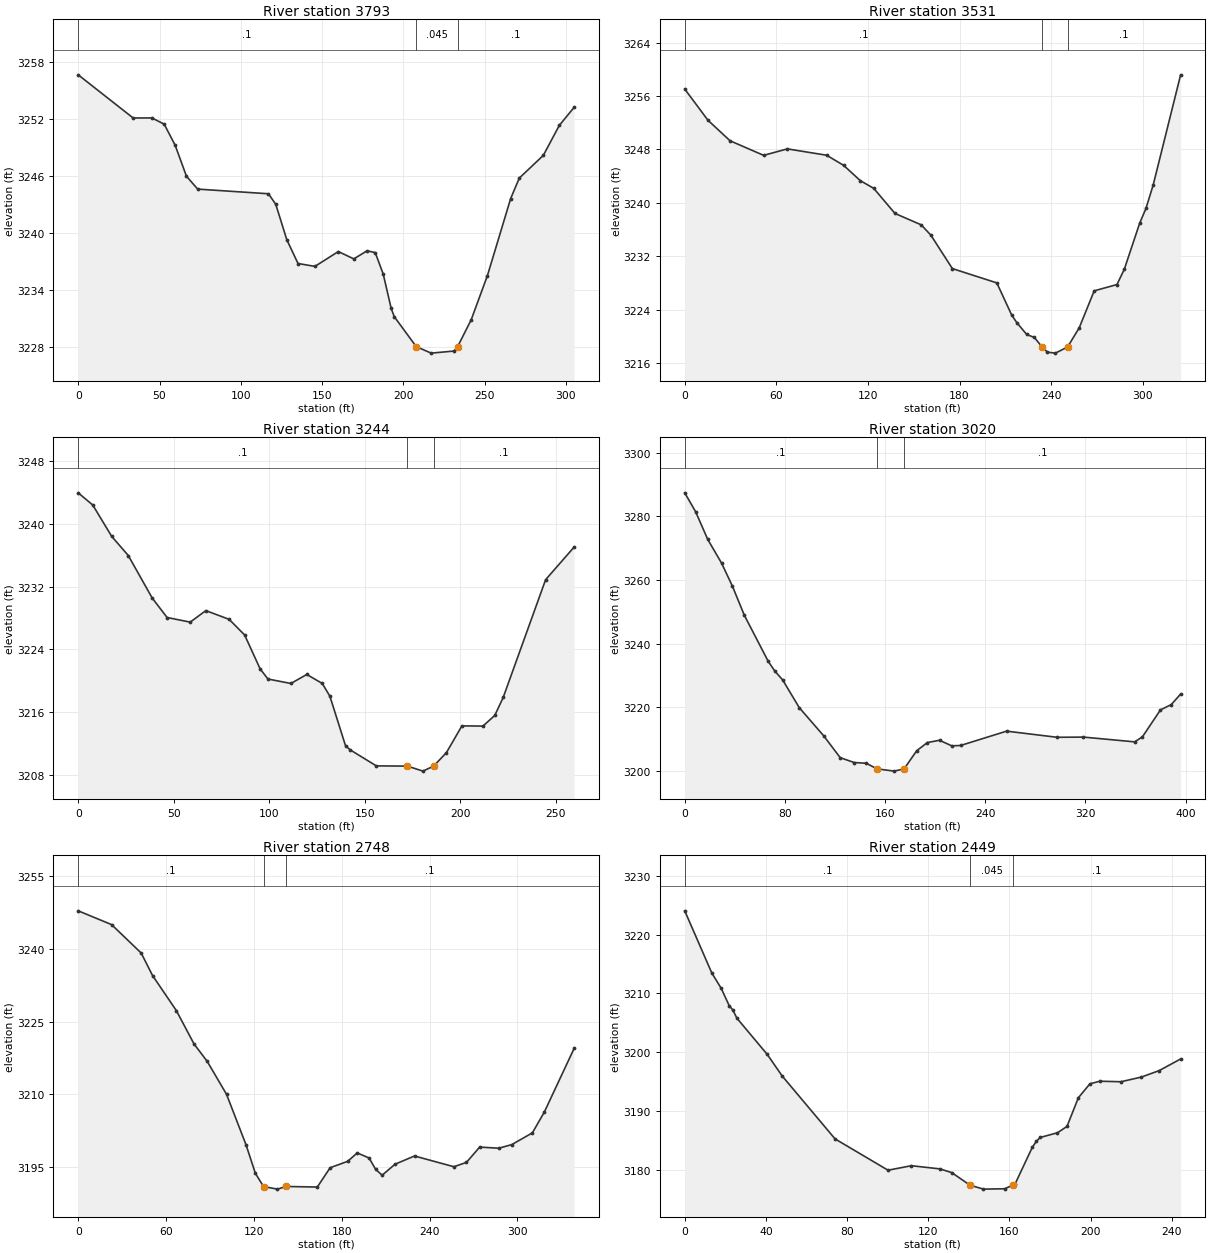
Type RM Length L Ch R = 1 ,3793    ,262.5,262.5,262.5
XS GIS Cut Line= 2
2196463.02562937534108.806407695 2196285.1090904534356.597759001
#Sta/Elev= 30
       0 3256.64    33.8 3252.09    45.3  3252.1    52.9 3251.44    59.6 3249.23
    66.6 3245.95    73.5  3244.6     117 3244.11   121.5    3243   128.3 3239.27
   135.2 3236.76   145.6 3236.46     160 3238.02   169.5 3237.25   177.7  3238.1
   182.7 3237.91   187.6 3235.65   192.5 3232.03   194.4 3231.16  207.913228.006
   217.1 3227.32   231.2 3227.54  233.383228.008   241.7 3230.83   251.7 3235.49
     266 3243.61   271.3 3245.76   286.1 3248.16   295.9 3251.31     305 3253.21
#Mann= 3 ,-1,0
       0      .1       0  207.91    .045       0  233.38      .1       0
Bank Sta=207.91,233.38
XS Rating Curve= 0 ,0
Exp/Cntr(USF)=0,0
Exp/Cntr=0.3,0.1

Type RM Length L Ch R = 1 ,3531    ,286.9,286.9,286.9
XS GIS Cut Line= 4
2196308.35588589533967.6326132652196153.07852514534093.550809163
2196106.10386139534159.4458235962196068.97161625534182.914163356
#Sta/Elev= 30
       0 3257.04    15.2 3252.37    29.7 3249.29    51.7 3247.11    67.2 3248.08
    92.9 3247.13   104.1 3245.61     115 3243.32   123.8 3242.17   137.7 3238.41
   154.9  3236.7   161.2 3235.16   175.3 3230.15   204.4 3228.01   214.2 3223.17
   217.5 3222.06     224 3220.28     229 3219.84  234.093218.407   237.6 3217.63
   242.8 3217.49  250.763218.409   258.4 3221.29   268.2 3226.82   283.1 3227.76
   287.9 3230.04     298 3236.96   302.1 3239.16   306.8 3242.64   324.8 3259.17
#Mann= 3 ,-1,0
       0      .1       0  234.09    .045       0  250.76      .1       0
Bank Sta=234.09,250.76
XS Rating Curve= 0 ,0
Exp/Cntr(USF)=0,0
Exp/Cntr=0.3,0.1

Type RM Length L Ch R = 1 ,3244    ,224.4,224.4,224.4
XS GIS Cut Line= 3
2196185.94489629533912.196628811 2195982.3056275533876.560232074
2195934.80418399533899.444139164
#Sta/Elev= 30
       0 3243.94     7.6 3242.39    17.5  3238.4    26.2 3235.95    38.7 3230.54
    46.5 3228.05    58.6 3227.46    66.8 3228.93      79 3227.81    87.1 3225.82
    95.2  3221.5    99.3 3220.21   111.3 3219.64   119.6 3220.79   127.7 3219.65
   131.7 3218.02   139.9  3211.7   142.4 3211.17     156 3209.14172.2558 3209.11
   172.3 3209.11   180.4 3208.47  186.04 3209.12   192.7 3210.83   200.8 3214.24
   211.8 3214.21     218 3215.57   222.4 3217.86   244.6 3232.87   259.5 3237.02
#Mann= 3 ,-1,0
       0      .1       0   172.3    .045       0  186.04      .1       0
Bank Sta=172.2558,186.04
XS Rating Curve= 0 ,0
Exp/Cntr(USF)=0,0
Exp/Cntr=0.3,0.1

Type RM Length L Ch R = 1 ,3020    ,271.5,271.5,271.5
XS GIS Cut Line= 2
2196091.28374205533583.4346677592195765.98419555533809.500237079
#Sta/Elev= 30
       0 3287.39     8.7 3281.44    18.4 3272.72    29.4 3265.31    38.1 3258.03
    47.6  3248.9    66.7 3234.39      72 3231.33    78.2 3228.57    91.5 3219.84
   110.9 3211.04   124.2 3204.12   135.3  3202.6     145 3202.36  153.613200.601
   167.3 3199.89  175.243200.602   185.3 3206.31   193.8 3208.87   203.5 3209.59
   213.3 3207.84   220.3 3207.95   257.1 3212.46   297.4 3210.53   318.5 3210.59
   359.4 3209.09   365.6 3210.68     380 3219.14   388.6 3220.81   396.1 3224.11
#Mann= 3 ,-1,0
       0      .1       0  153.61    .045       0  175.24      .1       0
Bank Sta=153.61,175.24
XS Rating Curve= 0 ,0
Exp/Cntr(USF)=0,0
Exp/Cntr=0.3,0.1

Type RM Length L Ch R = 1 ,2748    ,298.7,298.7,298.7
XS GIS Cut Line= 2
2195785.97191498  533417.70218222195640.64404899  533723.6599109
#Sta/Elev= 30
       0 3247.89    22.8 3245.04      43 3239.17    50.8  3234.5      67 3227.28
    79.1 3220.37    88.1 3216.77   101.3 3209.96   114.6 3199.54     121 3193.62
  126.623190.878   136.1 3190.35   142.1  3190.9   163.3 3190.78   172.1 3194.78
   184.1  3196.1   190.6 3197.84   198.7 3196.78   203.1 3194.46   207.6 3193.23
   216.4  3195.5   229.7  3197.2   256.6 3194.98   265.2 3195.88   274.2 3199.04
   287.3 3198.81   296.1 3199.55   310.2 3201.98   318.3 3206.24   338.7 3219.43
#Mann= 3 ,-1,0
       0      .1       0  126.62    .045       0   142.1      .1       0
Bank Sta=126.62,142.1
XS Rating Curve= 0 ,0
Exp/Cntr(USF)=0,0
Exp/Cntr=0.3,0.1

Type RM Length L Ch R = 1 ,2449    ,287,287,287
XS GIS Cut Line= 2
2195576.69978795533268.3579824582195419.74569268533455.751659842
#Sta/Elev= 30
       0 3224.06    13.3  3213.5      18 3210.84    21.9 3207.91    23.7 3207.17
    25.7 3205.78    40.7 3199.59      48 3195.94    74.1 3185.21   100.2 3179.88
   111.7 3180.65   125.9  3180.1   131.6 3179.47  140.593177.337   147.2 3176.66
   157.6 3176.72  161.823177.337   162.8 3177.53   171.3 3183.78   173.3  3184.8
   175.2 3185.46   183.7 3186.26   188.4 3187.34     194 3192.22   199.7  3194.6
   204.6 3195.04     215 3194.95   225.1 3195.75   233.8 3196.84   244.4 3198.83
#Mann= 3 ,-1,0
       0      .1       0  140.59    .045       0  161.82      .1       0
Bank Sta=140.59,161.82
XS Rating Curve= 0 ,0
Exp/Cntr(USF)=0,0
Exp/Cntr=0.3,0.1