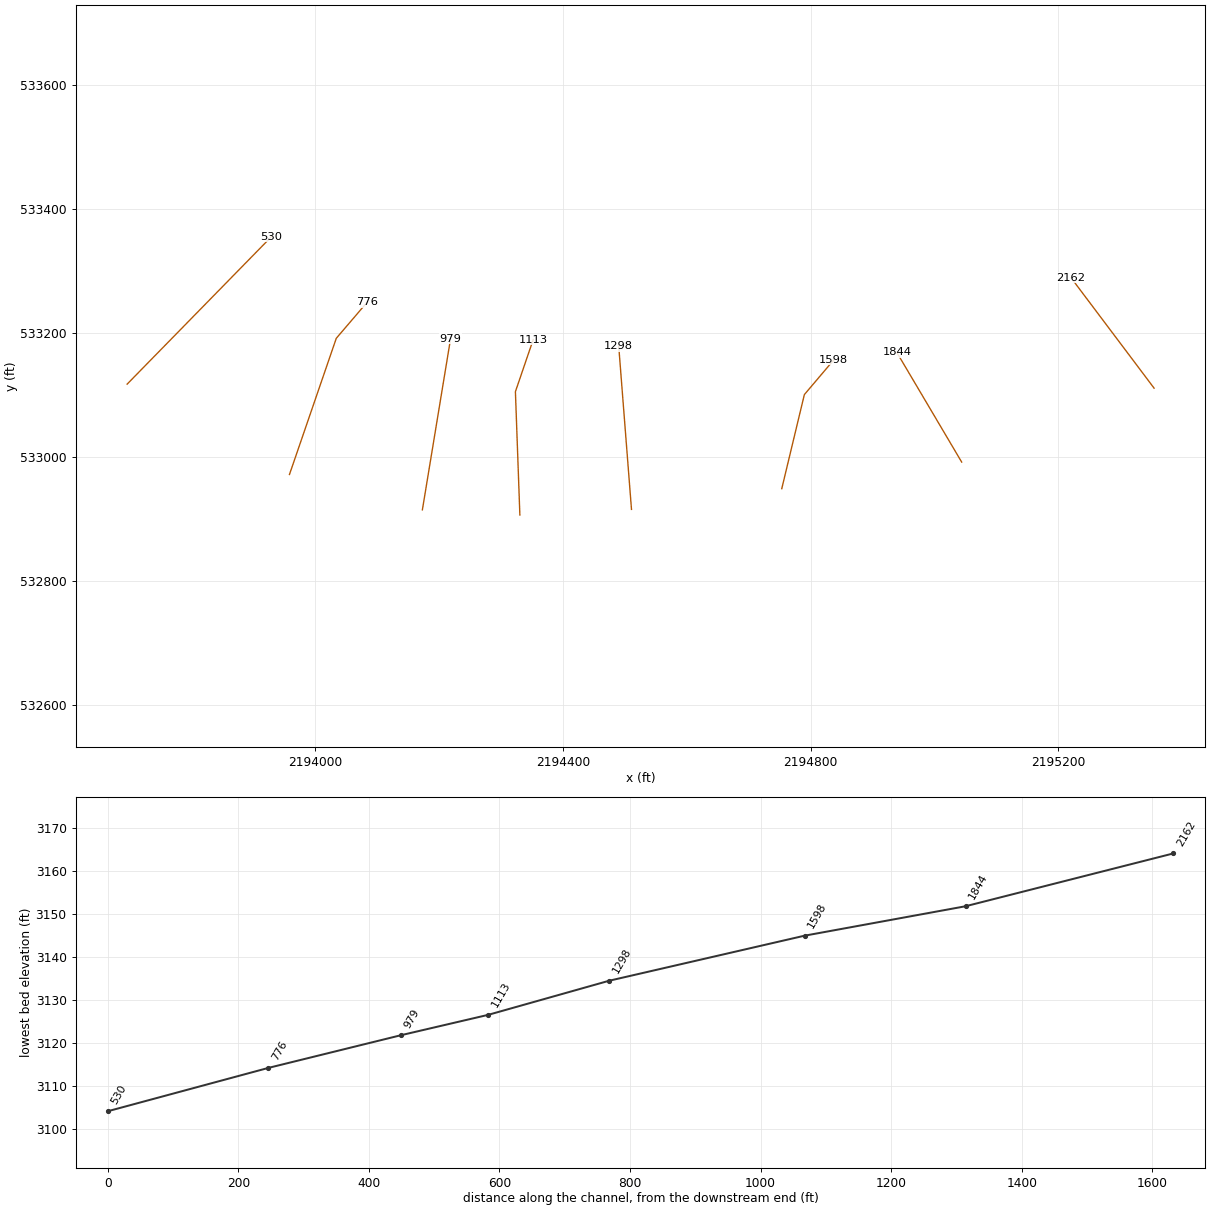
HEC-RAS study LEATHERWCK.prj: LEATHERWCK

--- LEATHERWCK.g01 (geometry) --- (continued)

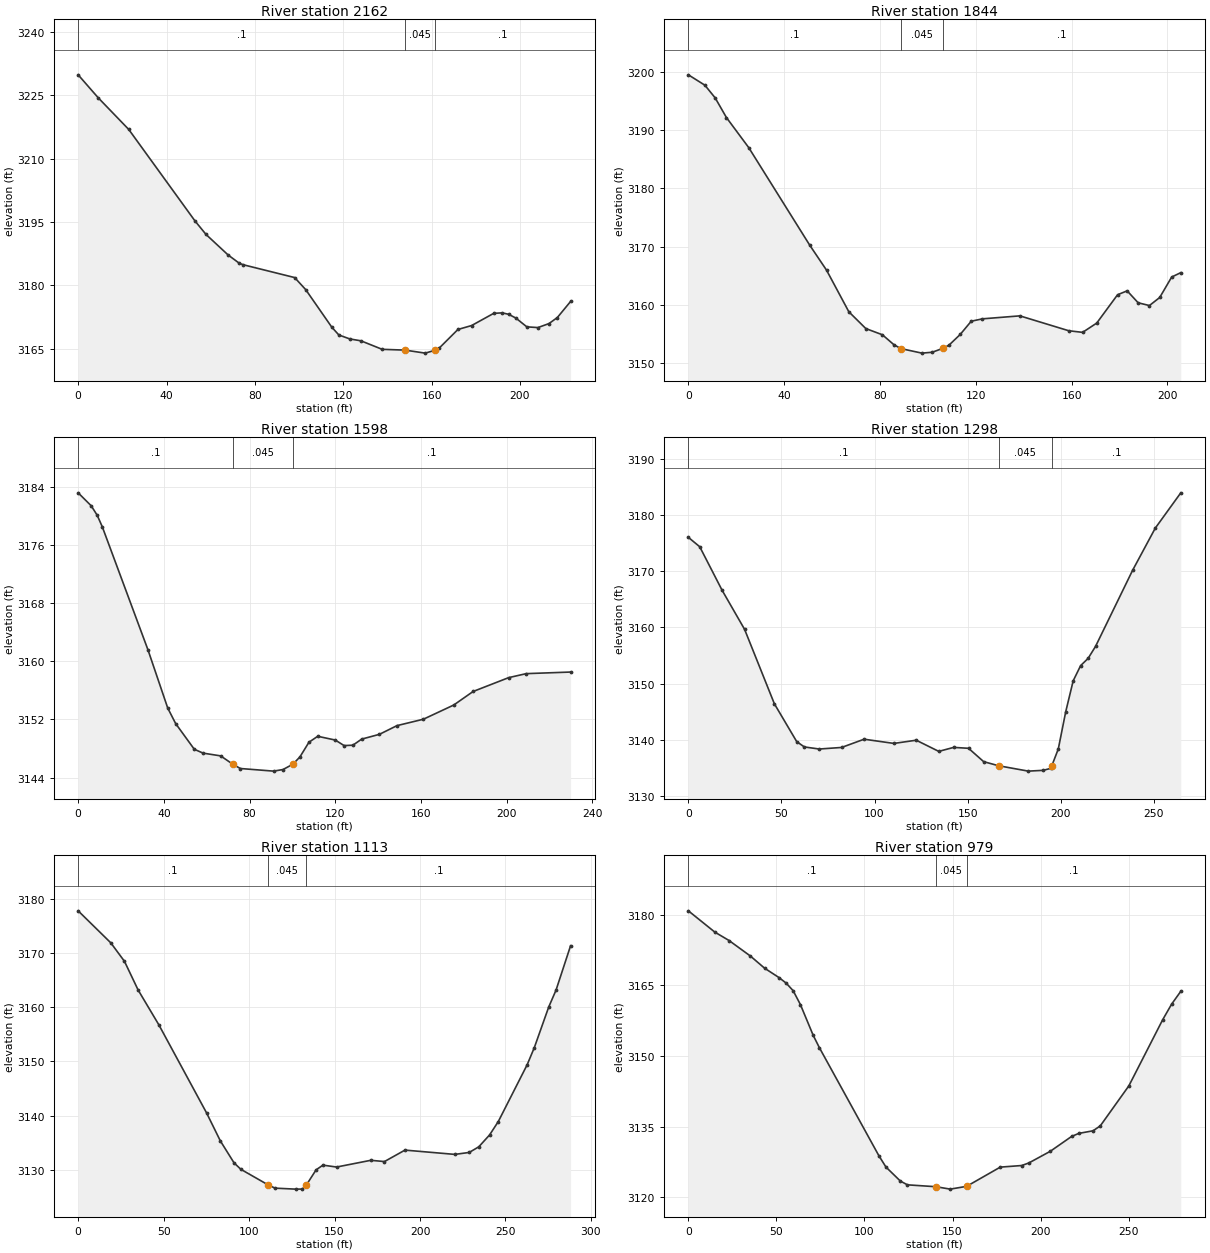
Type RM Length L Ch R = 1 ,2162    ,318.5,318.5,318.5
XS GIS Cut Line= 2
2195354.58596222533110.8800809572195220.60818576533288.987151225
#Sta/Elev= 30
       0 3229.79     9.1 3224.35    22.9 3216.88    52.9 3195.24    57.9 3192.05
    67.9  3187.2      73 3185.23    74.8 3184.89      98 3181.87     103 3179.02
   114.8 3170.15     118  3168.3     123 3167.36     128 3166.92   137.6 3164.91
     148 3164.72   157.1 3164.01  161.483164.676   163.3 3165.13   171.9  3169.6
   178.1 3170.53   188.1 3173.41   191.9 3173.53   194.8  3173.2   198.1 3172.31
   203.1 3170.22   208.1 3170.05   213.1 3170.99   216.9 3172.42   222.9 3176.22
#Mann= 3 ,-1,0
       0      .1       0     148    .045       0  161.48      .1       0
Bank Sta=148,161.48
XS Rating Curve= 0 ,0
Exp/Cntr(USF)=0,0
Exp/Cntr=0.3,0.1

Type RM Length L Ch R = 1 ,1844    ,246.4,246.4,246.4
XS GIS Cut Line= 2
2195044.00710097532991.4998448572194939.37103746533168.429915889
#Sta/Elev= 30
       0 3199.44     6.9 3197.66    11.2 3195.48    15.9 3192.11    25.2 3186.96
    50.7 3170.21    57.7 3165.94      67 3158.81    74.1 3155.93      81 3154.87
    85.8 3153.17    88.7  3152.5    97.5 3151.72   101.8 3151.87   106.2 3152.53
   108.8 3153.08   113.5 3154.92   118.1 3157.19   122.8  3157.6   138.4 3158.11
   158.8 3155.56   164.6 3155.28   170.5 3156.87   179.2 3161.73   183.2  3162.4
   187.8 3160.35   192.5 3159.88   196.8 3161.26   201.8 3164.77   205.6 3165.52
#Mann= 3 ,-1,0
       0      .1       0    88.7    .045       0   106.2      .1       0
Bank Sta=88.7,106.2
XS Rating Curve= 0 ,0
Exp/Cntr(USF)=0,0
Exp/Cntr=0.3,0.1

Type RM Length L Ch R = 1 ,1598    ,299.7,299.7,299.7
XS GIS Cut Line= 3
2194753.54408881532948.4946189532194790.02683772533100.416474605
2194837.58868477533156.539454126
#Sta/Elev= 30
       0 3183.22     6.1 3181.43     8.9 3180.12    11.3 3178.51    32.6 3161.57
    41.8 3153.57    45.5 3151.43    54.2 3147.89    58.3 3147.36    66.5 3146.98
   72.22 3145.82    75.7 3145.24    91.2 3144.88    95.6  3145.1   100.2 3145.83
   103.5 3146.84   107.7 3148.86   111.8 3149.68     120 3149.16   124.1  3148.4
   128.2 3148.45   132.3 3149.29   140.6 3149.95   148.8 3151.15   161.1 3152.03
   175.3 3153.99   184.3 3155.85   200.9 3157.76   209.1 3158.31   229.8 3158.53
#Mann= 3 ,0,0
       0      .1       0   72.22    .045       0   100.2      .1       0
Bank Sta=72.22,100.2
XS Rating Curve= 0 ,0
Exp/Cntr(USF)=0,0
Exp/Cntr=0.3,0.1

Type RM Length L Ch R = 1 ,1298    ,185,185,185
XS GIS Cut Line= 2
2194510.96591626532915.1079490292194490.34742284533178.793150124
#Sta/Elev= 30
       0 3176.06     6.1 3174.39    18.1 3166.64    30.2 3159.66    46.2 3146.39
    58.2 3139.65    62.3  3138.7    70.3 3138.33    82.3 3138.61    94.4 3140.08
   110.4 3139.33   122.4  3139.9   134.5 3137.91   142.5 3138.62   150.5 3138.46
   158.6 3136.08   166.6 3135.35   182.6 3134.39   190.6 3134.53   194.7 3134.89
  195.24 3135.36   198.7 3138.34   202.7 3144.99   206.7 3150.49   210.7  3153.2
   214.7 3154.48   218.7 3156.62   238.6 3170.18   250.8 3177.71   264.5    3184
#Mann= 3 ,0,0
       0      .1       0   166.6    .045       0  195.24      .1       0
Bank Sta=166.6,195.24
XS Rating Curve= 0 ,0
Exp/Cntr(USF)=0,0
Exp/Cntr=0.3,0.1

Type RM Length L Ch R = 1 ,1113    ,133.4,133.4,133.4
XS GIS Cut Line= 3
2194330.76726441532906.0589338512194323.57896018533105.174961066
 2194352.3321771533189.278120576
#Sta/Elev= 30
       0 3177.75    19.1 3171.85    27.1 3168.44    35.1 3163.15    47.2 3156.75
    75.1 3140.53    83.2 3135.35    91.2 3131.31    95.2 3130.12   111.2 3127.24
   115.2 3126.65   127.2 3126.47   131.2 3126.48   133.4 3127.17   139.2 3130.02
   143.2 3130.89   151.2 3130.54   171.2 3131.78   179.2 3131.55   191.2 3133.66
   220.4 3132.87   228.8 3133.23   234.4 3134.27   240.7 3136.45   245.8 3138.92
   262.7 3149.39   266.9 3152.56   275.3 3160.02   279.6 3163.15   288.1 3171.32
#Mann= 3 ,0,0
       0      .1       0   111.2    .045       0   133.4      .1       0
Bank Sta=111.2,133.4
XS Rating Curve= 0 ,0
Exp/Cntr(USF)=0,0
Exp/Cntr=0.3,0.1

Type RM Length L Ch R = 1 ,979     ,203.3,203.3,203.3
XS GIS Cut Line= 2
2194173.39887335532914.4232377352194218.85009051533190.346331935
#Sta/Elev= 30
       0  3180.8      15 3176.29    23.1  3174.5    35.2 3171.21    43.3 3168.62
    51.4 3166.65    55.5 3165.47    59.5 3163.85    63.6 3160.92    70.9 3154.36
    74.4 3151.75   108.2 3128.81   112.2 3126.42   120.4 3123.44   124.4 3122.65
   140.6 3122.25   148.7 3121.74     158 3122.33   177.1 3126.41   189.3 3126.75
   193.3 3127.29   205.5 3129.77   217.6 3132.92   221.7 3133.57   229.8 3134.12
   233.9 3135.17   250.1 3143.65   269.3 3157.68   274.4    3161   279.6 3163.72
#Mann= 3 ,-1,0
       0      .1       0   140.6    .045       0     158      .1       0
Bank Sta=140.6,158
XS Rating Curve= 0 ,0
Exp/Cntr(USF)=0,0
Exp/Cntr=0.3,0.1

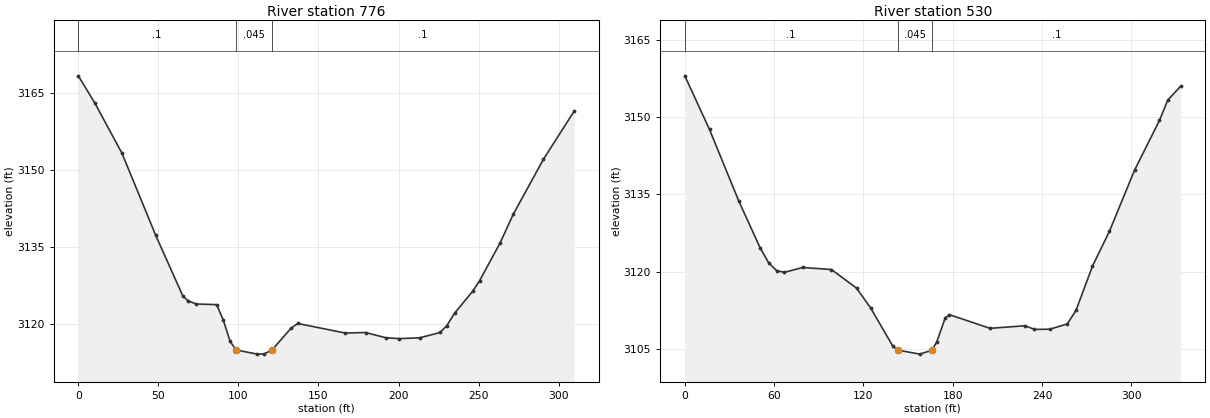
Type RM Length L Ch R = 1 ,776     ,246.1,246.1,246.1
XS GIS Cut Line= 3
2193958.84209665532971.4974541972194034.41258697533191.338880568
2194084.61675886533249.998491931
#Sta/Elev= 30
       0 3168.36    10.2 3163.12    27.2 3153.31    48.3 3137.31    65.2 3125.51
    68.5 3124.51    73.7  3123.9    86.4 3123.77    90.5  3120.8    94.8 3116.62
   98.543114.941   111.8 3114.13     116 3114.16     121 3114.94   132.9  3119.2
   137.1  3120.1   166.7 3118.24   179.4 3118.34   192.1 3117.32   200.6 3117.15
   213.3 3117.31     226 3118.35   230.2  3119.7     235  3122.1   246.4 3126.42
   250.7 3128.47   263.4 3135.78   271.7  3141.4   290.5  3152.1   309.7 3161.47
#Mann= 3 ,-1,0
       0      .1       0   98.54    .045       0     121      .1       0
Bank Sta=98.54,121
XS Rating Curve= 0 ,0
Exp/Cntr(USF)=0,0
Exp/Cntr=0.3,0.1

Type RM Length L Ch R = 1 ,530     ,,,
XS GIS Cut Line= 2
2193696.77353706533117.3262506342193929.63634022 533355.32573328
#Sta/Elev= 30
       0 3157.98    16.6 3147.58    36.2 3133.75    50.6 3124.65    56.3 3121.76
    61.7 3120.22    66.9  3119.9    79.2 3120.84    98.5 3120.44   115.4 3116.83
     125 3112.91   139.7  3105.6  142.883104.837   157.9 3104.05   166.13104.836
   169.2 3106.41   174.8 3110.97   177.7  3111.7     205 3109.05   228.6 3109.55
   234.8 3108.84   245.1 3108.88   256.9  3109.9   262.8 3112.57   273.8  3121.1
   285.2 3127.87   302.1 3139.72   318.8 3149.35   324.4 3153.28     333 3155.96
#Mann= 3 ,-1,0
       0      .1       0  142.88    .045       0   166.1      .1       0
Bank Sta=142.88,166.1
XS Rating Curve= 0 ,0
Exp/Cntr(USF)=0,0
Exp/Cntr=0.3,0.1
LCMann Table=0

Chan Stop Cuts=-1
Use User Specified Reach Order=0
Composite Channel Slope=5